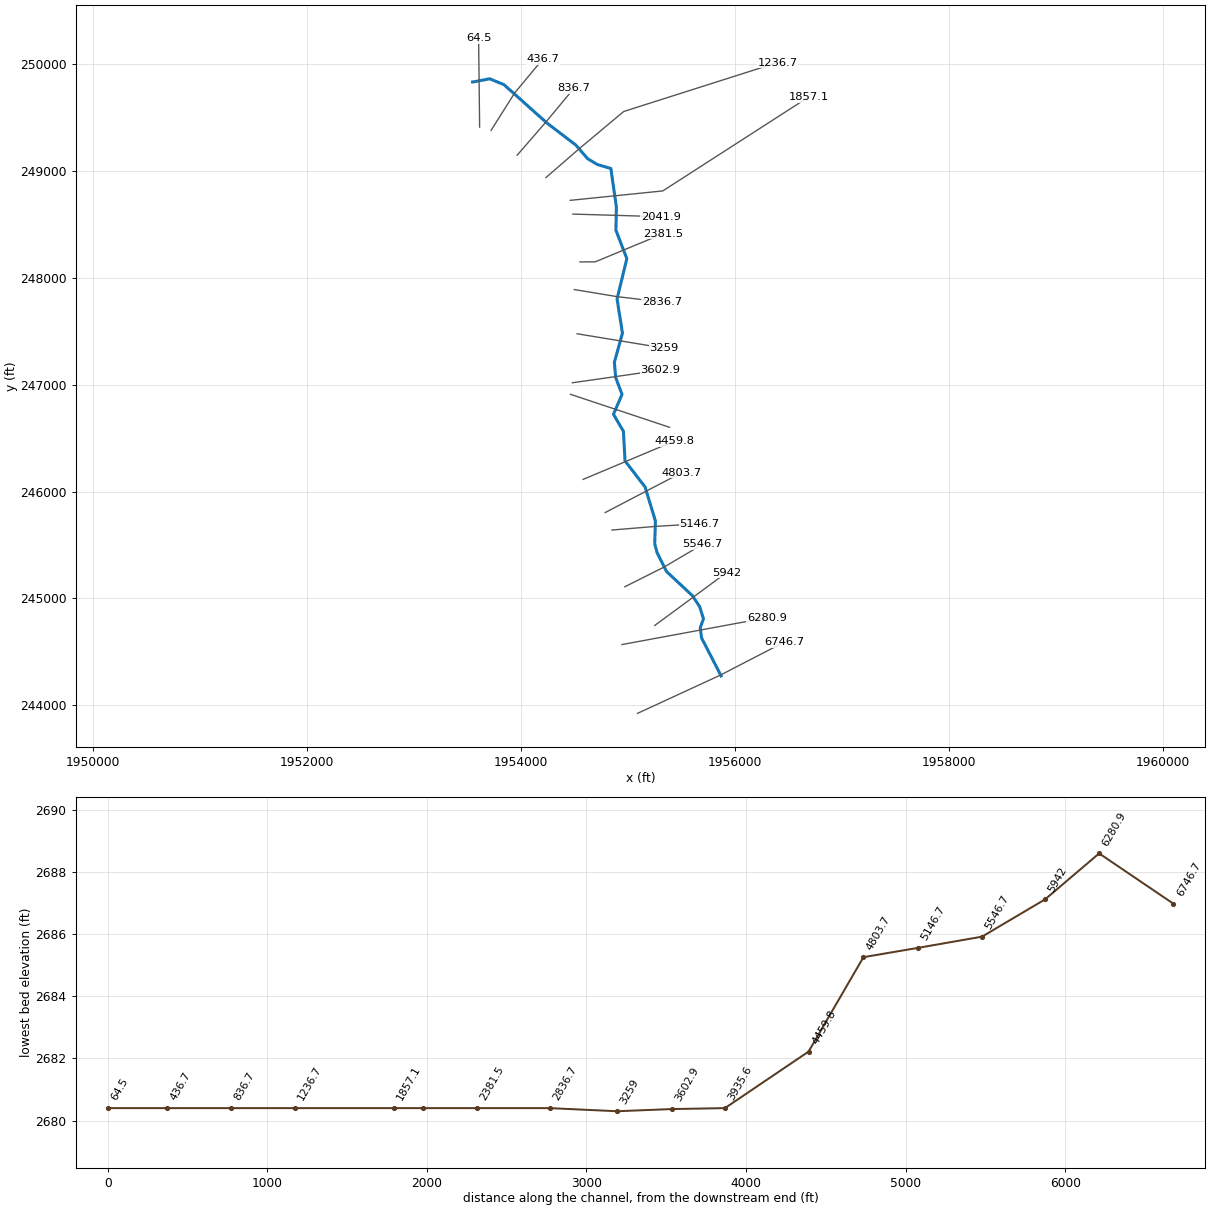
--- CprCrk.prj (project) ---

Proj Title=CprCrk
Current Plan=p01
Default Exp/Contr=0,0
English Units
Geom File=g01
Flow File=f01
Plan File=p01
BEGIN DESCRIPTION:
END DESCRIPTION:
DSS Export Rating Curves= 0
DSS Export Rating Curve Sorted= 0
DSS Export Volume Flow Curves= 0
DXF OffsetX= 0
DXF OffsetY= 0
DXF ScaleX= 0
DXF ScaleY= 0

--- CprCrk.p01 (plan) ---

Plan Title=Floodplain
Program Version=4.00
Geom File=g01
Flow File=f01
K Sum by GR=0
Std Step Tol=0.01
Critical Tol=0.01
Num of Std Step Trials=20
Max Error Tol=0.3
Flow Tol Ratio=0.001
Split Flow NTrial=30
Split Flow Tol=0.02
Split Flow Ratio=0.02
Log Output Level=0
Friction Slope Method=1
Unsteady Friction Slope Method=2
Unsteady Bridges Friction Slope Method=1
Global Log Level=0
CheckData=False
Run HTab=0
Run UNet=0
Run PostProcess=0
UNET Theta=0
UNET Theta Warmup=0
UNET ZTol=0
UNET ZSATol=0
UNET MxIter=0
UNET MaxInSteps=0
UNET DtIC=0
UNET DtMin=0
UNET MaxCRTS=0
UNET WFStab=0
UNET SFStab=0
UNET WFX=0
UNET SFX=0
UNET DSS MLevel=0
UNET DZMax Abort=0
UNET Convert EG Bridges=0
UNET Use Existing IB Tables=0
UNET Froude Limit=0
UNET Froude Power=0
Write IC File=0
Echo Input=False
Echo Output=False
Write Detailed=0

--- CprCrk.f01 (steady flow) ---

Flow Title=NFF Regression Equation
Program Version=4.00
Number of Profiles=1
Profile Names=P100yr
River Rch & RM=CprCrk,Main      ,6746.7
844.0682
River Rch & RM=CprCrk,Main      ,5546.7
891.3210
River Rch & RM=CprCrk,Main      ,1236.7
969.9025
River Rch & RM=CprCrk,Main      ,836.7
1205.298
River Rch & RM=CprCrk,Main      ,64.5
1211.989
Boundary for River Rch & Prof#=CprCrk,Main      ,1
Up Type=0
Dn Type=3
Dn Slope=0.000001

--- CprCrk.g01 (geometry) ---

Geom Title=USGS 3m DEM
Program Version=4.10

River Reach=CprCrk          ,Main
Reach XY= 30
     1955871.405       244273.04      1955688.17      244629.384
     1955676.447      244725.773     1955706.038      244807.772
     1955671.714      244919.608     1955603.806      245023.805
     1955361.857      245250.264     1955273.957      245424.215
     1955250.794      245510.059     1955257.029      245724.838
     1955160.641      246042.663     1954973.139      246287.263
     1954958.334      246563.861     1954864.988      246723.729
     1954945.285      246910.313     1954885.612      247067.986
     1954873.722      247210.221     1954949.164      247485.172
     1954898.449      247804.538     1954990.186      248181.583
     1954887.991      248447.594      1954892.27      248667.671
     1954840.671       249025.78     1954714.151      249063.521
     1954624.026      249117.385     1954513.239      249245.446
     1954241.753      249453.166     1953841.504      249811.514
     1953708.401      249865.866     1953548.648      249835.659

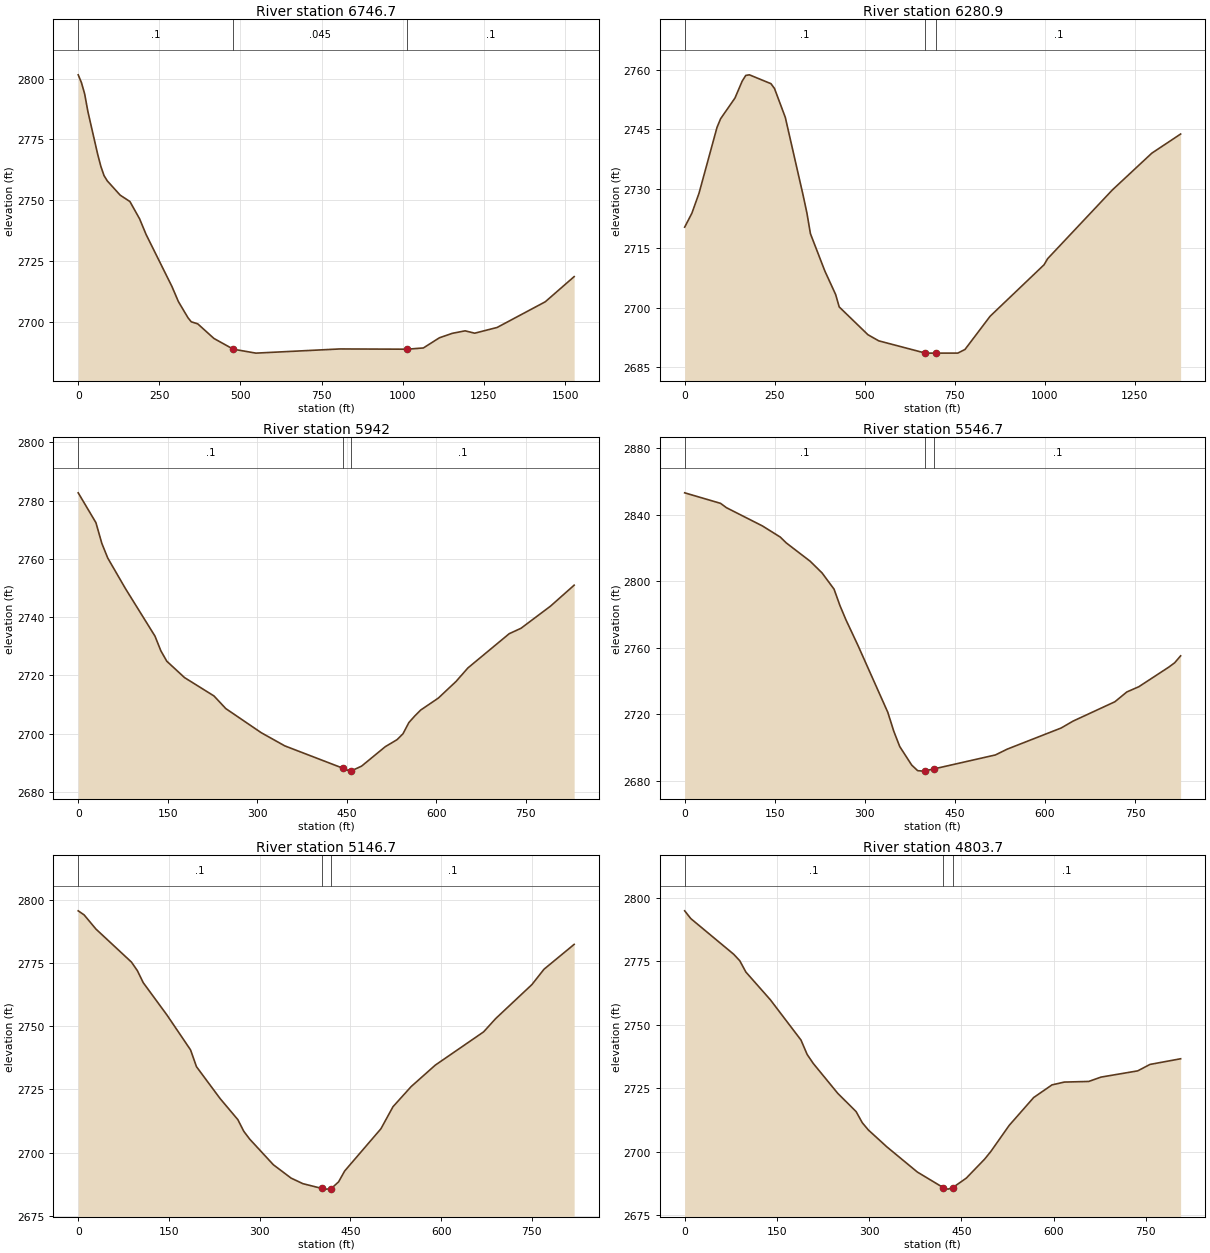
Type RM Length L Ch R = 1 ,6746.7  ,471.3,465.6,459
XS GIS Cut Line= 3
       1955089.5      243922.422     1955866.467      244281.735
     1956463.129       244591.13
#Sta/Elev= 30
       0 2801.59      10 2798.37    19.9 2793.71    29.9 2786.42    59.7 2769.03
    69.7 2763.92    79.6 2760.08    89.6 2757.91   129.4 2752.03   159.3 2749.41
   189.1  2742.3     209 2735.89   288.7 2714.45   308.6 2708.23   338.4 2701.52
   348.4 2699.88   368.3 2699.04   418.1 2693.03   477.8  2688.6   547.5 2686.98
   806.3  2688.7  1014.2  2688.6  1063.6 2689.11    1113  2693.3  1152.6 2695.13
  1192.1 2696.16  1221.7 2695.19  1290.9 2697.56  1439.2 2708.13  1528.1 2718.49
#Mann= 3 , 0 , 0
       0      .1       0   477.8    .045       0  1014.2      .1       0
Bank Sta=477.8,1014.2
XS Rating Curve= 0 ,0
Exp/Cntr=0.3,0.1

Type RM Length L Ch R = 1 ,6280.9  ,328.1,338.8,349.6
XS GIS Cut Line= 2
     1954944.654      244566.989      1956298.97      244818.057
#Sta/Elev= 30
       0 2720.37      20 2723.88    39.9 2728.94    89.8 2745.53    99.8 2747.71
   139.7 2752.93   159.7 2757.19   169.7 2758.63   179.7 2758.78   239.6 2756.55
   249.5 2755.33   279.5 2748.04   329.4 2728.23   339.4 2723.98   349.3 2718.71
   389.3 2709.31   419.2  2703.4   429.2 2700.25     509 2693.24     539  2691.7
   668.7  2688.6   698.7  2688.6   758.6 2688.61   778.5 2689.52   848.4 2697.91
   998.1 2710.88  1008.1 2712.42  1187.8 2729.75  1297.5 2739.03  1377.4 2743.85
#Mann= 3 , 0 , 0
       0      .1       0   668.7    .045       0   698.7      .1       0
Bank Sta=668.7,698.7
XS Rating Curve= 0 ,0
Exp/Cntr=0.3,0.1

Type RM Length L Ch R = 1 ,5942    ,398.8,395,392.7
XS GIS Cut Line= 2
     1955251.136      244746.001     1955919.811      245239.287
#Sta/Elev= 30
       0 2782.65    29.7  2772.4    39.6 2765.28    49.5 2760.26    79.1 2749.79
   128.6 2733.47   138.5 2728.41   148.4 2724.85   178.1 2719.23   227.5 2712.92
   247.3 2708.58   306.7  2700.3   346.2 2695.78   442.8 2688.17     455 2687.12
   457.8 2687.23   474.8 2688.84   514.4  2695.5   534.2 2697.92   544.1 2699.93
     554 2703.79   563.8 2706.03   573.7 2708.07   603.4  2712.2   633.1 2717.92
   652.9 2722.54   722.1 2734.29   741.9 2736.16   791.4 2743.77   830.9 2750.95
#Mann= 3 , 0 , 0
       0      .1       0   442.8    .045       0   457.8      .1       0
Bank Sta=442.8,457.8
XS Rating Curve= 0 ,0
Exp/Cntr=0.3,0.1

Type RM Length L Ch R = 1 ,5546.7  ,408.7,399.9,389.2
XS GIS Cut Line= 3
     1954971.635      245108.466     1955336.104      245291.829
     1955696.105       245504.31
#Sta/Elev= 30
       0 2853.03    59.7 2846.72    69.7 2844.08   129.4 2833.17   159.2 2826.47
   169.2 2822.95     209 2811.96   228.9  2804.9   248.8 2795.18   258.7 2785.24
   268.7  2776.7   288.6 2761.41   338.3 2721.25   348.3 2709.84   358.2 2700.67
   378.1 2689.56   388.1 2686.19     398 2685.92   400.5  2686.1   415.5 2687.28
   517.5 2695.63   537.4 2699.15     627 2711.81   646.9 2715.96   716.5 2727.57
   736.4 2733.45   756.4  2736.6   806.1 2748.32   816.1 2750.98     826 2755.14
#Mann= 3 , 0 , 0
       0      .1       0   400.5    .045       0   415.5      .1       0
Bank Sta=400.5,415.5
XS Rating Curve= 0 ,0
Exp/Cntr=0.3,0.1

Type RM Length L Ch R = 1 ,5146.7  ,333.7,343,352.8
XS GIS Cut Line= 3
     1954851.047      245639.732      1955260.16       245673.69
     1955668.715      245698.703
#Sta/Elev= 30
       0 2795.65     9.8 2794.03    29.3 2788.44      88 2775.37    97.7 2772.02
   107.5 2767.23   146.6 2754.47   185.7 2740.64   195.5 2733.99   234.6 2721.37
   263.9 2713.04   273.7 2708.44   283.4 2705.36   322.6  2695.2   351.9 2689.92
   371.4 2687.72     403 2685.82   410.5 2685.56     418 2685.71   430.5 2688.47
   440.5 2692.75   500.4 2709.44   520.3 2718.15   550.3 2726.11   590.2  2734.6
   670.1 2747.76   690.1 2753.03     750 2766.48   769.9 2772.53   819.8 2782.38
#Mann= 3 , 0 , 0
       0      .1       0     403    .045       0     418      .1       0
Bank Sta=403,418
XS Rating Curve= 0 ,0
Exp/Cntr=0.3,0.1

Type RM Length L Ch R = 1 ,4803.7  ,345.8,343.8,341.9
XS GIS Cut Line= 2
     1954787.631      245803.359     1955502.313      246177.201
#Sta/Elev= 30
       0 2794.97      10  2791.9    79.7 2777.86    89.6 2775.29    99.6 2770.82
   139.4 2759.89   189.2 2744.02   199.2 2738.35   209.1 2734.82   248.9 2723.04
   278.8 2715.84   288.8 2711.46   298.7 2708.59   328.6 2701.97   378.4    2692
   420.7 2685.83   428.2 2685.26   435.7 2685.81     458 2689.59   487.9  2697.1
   497.9 2700.09   527.7 2710.36   567.6 2721.37   597.4 2726.35   617.4 2727.46
   657.2 2727.71   677.1 2729.42   736.8 2731.88   756.8 2734.42   806.6 2736.65
#Mann= 3 , 0 , 0
       0      .1       0   420.7    .045       0   435.7      .1       0
Bank Sta=420.7,435.7
XS Rating Curve= 0 ,0
Exp/Cntr=0.3,0.1

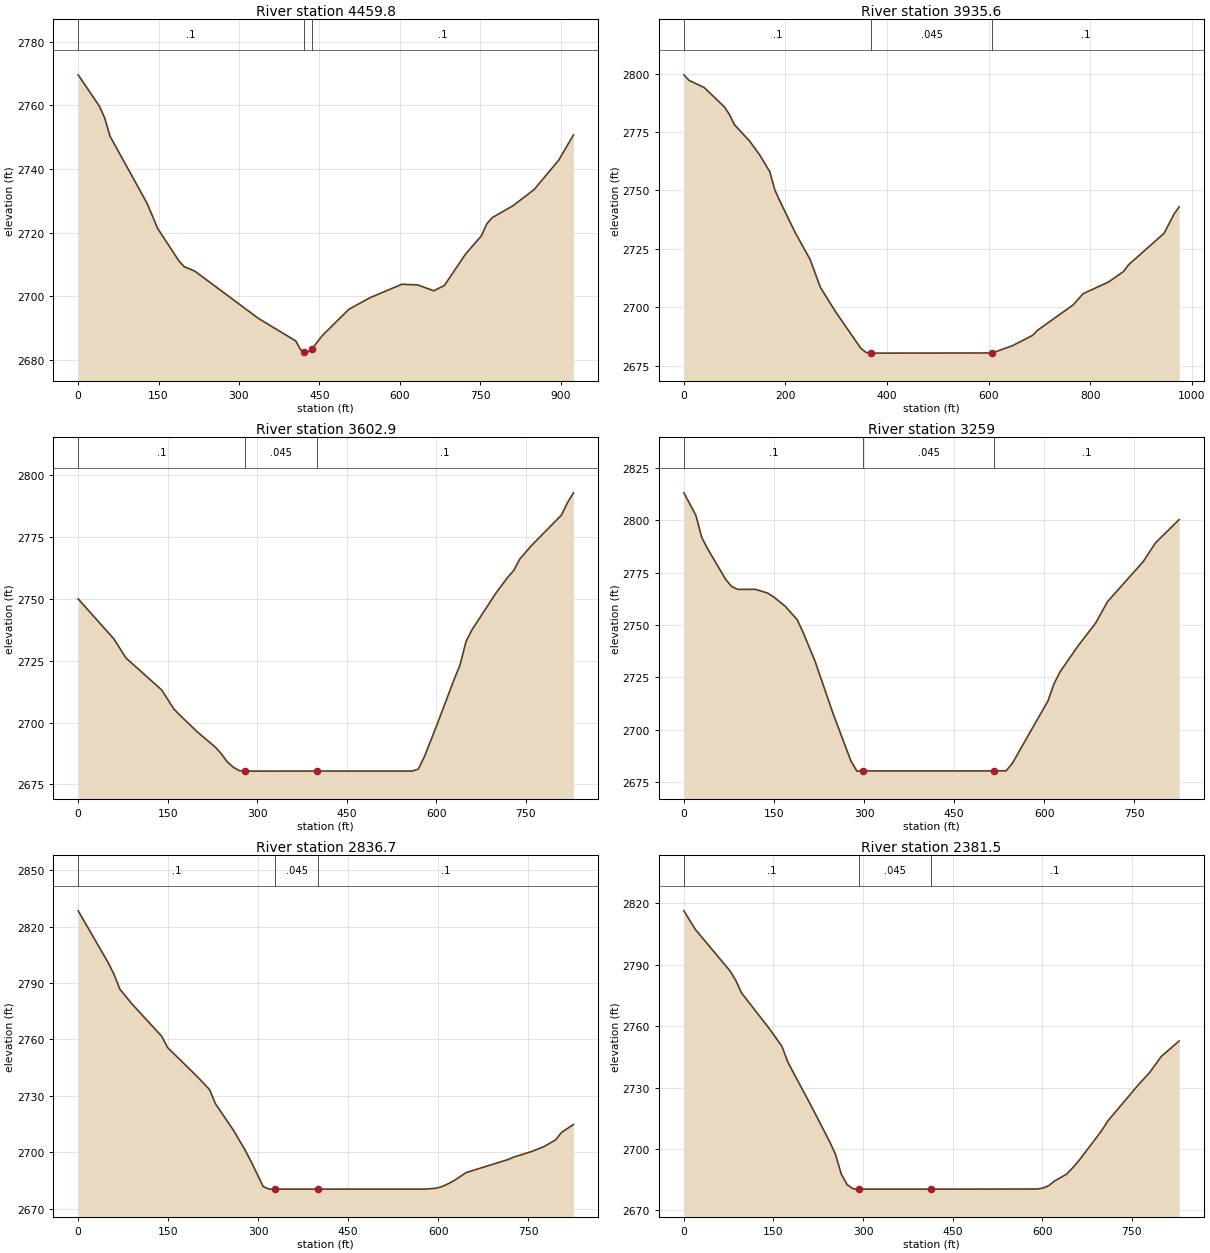
Type RM Length L Ch R = 1 ,4459.8  ,540.5,524.2,507.8
XS GIS Cut Line= 3
     1954581.684       246114.12     1955357.467      246440.339
     1955434.718      246469.308
#Sta/Elev= 30
       0 2769.59    39.6 2759.74    49.5 2756.04    59.4 2750.33   128.7 2729.21
   148.5  2721.3   188.1 2711.15     198 2709.35   217.8 2707.95   336.6 2693.09
   405.9 2686.06   415.8 2683.07   420.8 2682.64   425.7 2682.22   435.8 2683.44
   455.4 2687.71     505 2695.97   544.6 2699.63     604 2703.85   633.7 2703.63
   663.4  2701.8   683.2 2703.43   722.8 2713.31   752.5 2719.07   762.4 2722.81
   772.3 2724.72   811.9 2728.55   850.8 2733.59   896.6 2742.79   924.1 2750.72
#Mann= 3 , 0 , 0
       0      .1       0   420.8    .045       0   435.8      .1       0
Bank Sta=420.8,435.8
XS Rating Curve= 0 ,0
Exp/Cntr=0.3,0.1

Type RM Length L Ch R = 1 ,3935.6  ,321.8,332.3,342.8
XS GIS Cut Line= 2
     1954463.577      246910.781      1955388.85      246602.084
#Sta/Elev= 30
       0 2799.47      10 2797.12    39.8 2794.07    79.6 2785.78    89.6 2782.54
    99.5 2778.12   129.4 2771.14   149.3  2765.2   169.2 2758.02   179.2 2750.18
   189.1 2745.43     219 2732.09   248.8 2720.37   268.7  2708.6   298.6 2698.14
   348.4  2682.5   358.3 2680.75   368.3  2680.4   607.1 2680.47     647 2683.56
   686.8 2687.99   696.7  2690.2   766.4 2700.99   786.3 2705.84   836.1  2710.8
   865.9 2715.32   875.9 2718.24   945.6 2731.64   965.5 2739.92   975.4 2742.99
#Mann= 3 , 0 , 0
       0      .1       0   368.3    .045       0   607.1      .1       0
Bank Sta=368.3,607.1
XS Rating Curve= 0 ,0
Exp/Cntr=0.3,0.1

Type RM Length L Ch R = 1 ,3602.9  ,350.4,343.4,336.5
XS GIS Cut Line= 2
     1954481.493      247019.093     1955302.864      247136.454
#Sta/Elev= 30
       0    2750      60 2733.78      80 2726.13     140 2713.16   159.9 2705.64
   169.9 2703.11   199.9 2696.17   229.9 2690.04   239.9 2687.35   249.9 2684.07
   259.9 2681.97   269.9 2680.56   279.9 2680.37   399.6  2680.4   559.8  2680.4
   569.8 2681.19   579.8 2686.09   599.8  2698.3   629.8 2717.42   639.8 2723.39
   649.8  2732.8   659.8 2737.54   699.8 2752.34   719.8  2758.8   729.8 2761.53
   739.7 2766.08   759.7 2771.65   809.7  2783.9   819.7  2788.9   829.7 2792.89
#Mann= 3 , 0 , 0
       0      .1       0   279.9    .045       0   399.6      .1       0
Bank Sta=279.9,399.6
XS Rating Curve= 0 ,0
Exp/Cntr=0.3,0.1

Type RM Length L Ch R = 1 ,3259    ,422.2,422.3,423.3
XS GIS Cut Line= 2
      1954525.37      247477.887      1955338.82      247343.786
#Sta/Elev= 30
       0 2813.03    19.9 2802.32    29.8 2791.71    39.7 2786.25    69.5 2771.78
    79.5 2768.35    89.4 2766.99   119.2    2767   139.1 2765.24     149  2763.5
   168.9 2758.89   188.7 2752.47   198.7 2746.31   218.5 2732.58   248.3 2707.76
   278.1 2685.13     288  2680.3     298  2680.4   516.5  2680.4   536.4 2680.47
   546.3 2683.82   605.9 2713.72   615.8 2721.74   625.8 2727.49   655.6 2739.84
   685.4 2750.92   705.2 2761.14   764.8  2780.3   784.7 2789.06   824.4 2800.27
#Mann= 3 , 0 , 0
       0      .1       0     298    .045       0   516.5      .1       0
Bank Sta=298,516.5
XS Rating Curve= 0 ,0
Exp/Cntr=0.3,0.1

Type RM Length L Ch R = 1 ,2836.7  ,441.6,454.3,466
XS GIS Cut Line= 3
     1954499.031      247891.918     1954901.626      247825.449
     1955316.286       247776.12
#Sta/Elev= 30
       0 2828.43    49.8 2800.99    59.7 2794.67    69.7  2786.7    89.6 2778.94
   139.3 2761.68   149.3 2755.61     199 2740.09     219 2733.36   228.9 2725.79
   258.8 2711.75   278.7 2700.92   288.6 2694.86   308.5 2681.76   318.5  2680.4
   328.4  2680.4   400.5  2680.4   577.1  2680.4     597 2680.88   606.9 2681.82
   616.8 2683.25   626.8 2684.95   646.7 2689.22   716.3  2696.1   726.2 2697.46
     756 2700.41   775.9 2702.94   795.8 2706.55   805.7 2710.54   825.6 2714.77
#Mann= 3 , 0 , 0
       0      .1       0   328.4    .045       0   400.5      .1       0
Bank Sta=328.4,400.5
XS Rating Curve= 0 ,0
Exp/Cntr=0.3,0.1

Type RM Length L Ch R = 1 ,2381.5  ,349.1,339.5,329.9
XS GIS Cut Line= 3
     1954551.514      248150.512        1954696.      248151.943
     1955328.175      248415.378
#Sta/Elev= 30
       0 2816.25    19.3 2807.12    77.1 2786.98    86.7 2782.44    96.3 2776.28
   144.5 2758.22   164.3 2750.03   174.3 2742.27     214 2720.58   243.8 2703.72
   253.7 2697.52   263.6 2687.73   273.5 2682.57   283.4 2680.57   293.4  2680.4
   414.4  2680.4   591.2 2680.45   601.1  2680.9     611 2682.08   620.9 2684.39
   640.8 2687.67   650.7 2690.66   660.6 2693.99   690.4 2705.38   700.3 2709.26
   710.2 2713.76   759.9 2730.93   779.7 2737.22   799.6 2745.22   829.4 2752.71
#Mann= 3 , 0 , 0
       0      .1       0   293.4    .045       0   414.4      .1       0
Bank Sta=293.4,414.4
XS Rating Curve= 0 ,0
Exp/Cntr=0.3,0.1

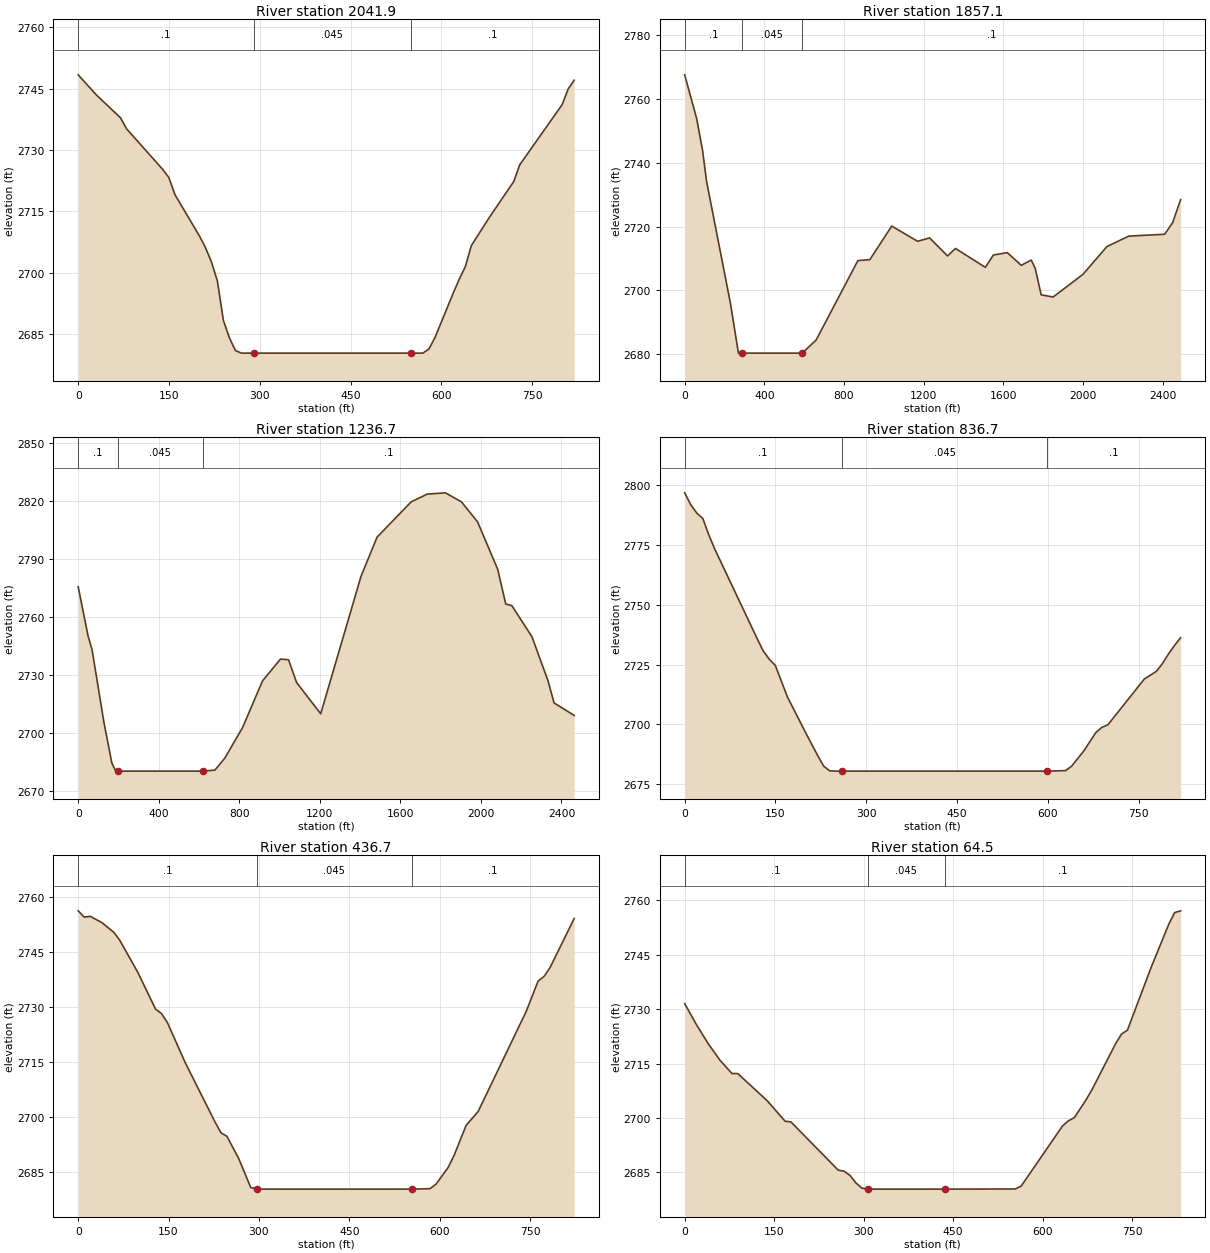
Type RM Length L Ch R = 1 ,2041.9  ,181.6,184.6,187.5
XS GIS Cut Line= 2
     1954486.155       248598.93     1955305.329      248574.461
#Sta/Elev= 30
       0 2748.35      30 2743.44      70 2737.84      80 2735.16   139.9 2725.21
   149.9 2723.24   159.9 2719.08   199.9 2709.11   209.9  2706.3   219.9 2702.77
   229.9 2698.06   239.9  2688.4   249.9 2684.11   259.8 2681.03   269.8  2680.4
   289.8  2680.4   549.7  2680.4   569.7  2680.4   579.7 2681.45   589.7 2684.26
   619.6 2695.02   629.6 2698.44   639.6 2701.48   649.6 2706.64   679.6 2713.59
   719.6 2722.27   729.6 2726.38   799.6 2741.06   809.6 2744.89   819.5 2747.04
#Mann= 3 , 0 , 0
       0      .1       0   289.8    .045       0   549.7      .1       0
Bank Sta=289.8,549.7
XS Rating Curve= 0 ,0
Exp/Cntr=0.3,0.1

Type RM Length L Ch R = 1 ,1857.1  ,603.6,619.8,634.9
XS GIS Cut Line= 3
     1954460.897      248727.518     1955326.083      248815.824
     1956687.641       249694.56
#Sta/Elev= 30
       0 2767.48      60 2753.84      90 2743.79     110 2734.12   229.9 2695.96
   269.9  2680.4   289.9  2680.4   589.8  2680.4   659.8 2684.47   869.7 2709.35
   929.7 2709.64  1039.7 2720.15  1169.8 2715.39  1229.8 2716.46  1319.8 2710.81
  1359.8 2713.15  1509.9 2707.24  1549.9  2711.1  1619.9 2711.85  1689.9 2707.87
    1740 2709.52    1760 2706.96    1790 2698.65    1850 2697.95    2000 2705.06
  2120.1 2713.74  2230.1 2717.02  2410.2 2717.59  2450.2 2721.23  2490.2 2728.43
#Mann= 3 , 0 , 0
       0      .1       0   289.9    .045       0   589.8      .1       0
Bank Sta=289.9,589.8
XS Rating Curve= 0 ,0
Exp/Cntr=0.3,0.1

Type RM Length L Ch R = 1 ,1236.7  ,396.6,399.8,403.9
XS GIS Cut Line= 4
     1954233.991      248940.945     1954545.726      249211.758
     1954960.882      249559.703     1956397.948       250018.05
#Sta/Elev= 30
       0 2775.59    49.2 2750.08    68.8 2743.11   127.8 2705.55   167.1 2684.57
   186.8  2680.4   196.6  2680.4   619.8  2680.4   678.9 2680.94   728.1 2687.12
   816.7 2702.97   915.2 2726.99  1004.6 2738.27  1044.5 2737.91  1084.5 2726.18
  1204.4 2710.01  1404.1 2780.87  1484.1 2801.21  1653.9 2819.48  1733.8 2823.46
  1823.7 2824.11  1903.6 2819.41  1983.5  2809.1  2083.4  2784.6  2123.4 2766.67
  2153.3 2765.88  2253.2 2749.86  2333.2 2727.06  2363.1 2715.64    2463 2709.17
#Mann= 3 , 0 , 0
       0      .1       0   196.6    .045       0   619.8      .1       0
Bank Sta=196.6,619.8
XS Rating Curve= 0 ,0
Exp/Cntr=0.3,0.1

Type RM Length L Ch R = 1 ,836.7   ,396.2,399.7,399.8
XS GIS Cut Line= 3
     1953965.525      249150.794     1954233.378      249460.412
     1954494.958      249776.213
#Sta/Elev= 30
       0 2796.82      10 2791.87      20 2788.33      30  2786.1    39.9 2779.21
    49.9  2773.2   119.8  2735.8   129.8 2730.66   139.8 2727.23   149.8  2724.6
   169.8 2711.42   199.7 2696.56   219.7 2686.95   229.7 2682.48   239.6 2680.52
   249.6  2680.4   259.6  2680.4   599.4  2680.4   629.4 2680.61   639.4 2682.48
   659.4 2688.79   679.4 2696.54   689.4  2698.7   699.4 2699.81   759.5 2718.92
   779.5 2722.14   789.5 2725.39   799.5 2729.44   809.5    2733   819.5 2736.22
#Mann= 3 , 0 , 0
       0      .1       0   259.6    .045       0   599.4      .1       0
Bank Sta=259.6,599.4
XS Rating Curve= 0 ,0
Exp/Cntr=0.3,0.1

Type RM Length L Ch R = 1 ,436.7   ,359.3,372,387.6
XS GIS Cut Line= 3
     1953721.454      249382.981     1953942.256      249734.083
     1954203.233      250048.443
#Sta/Elev= 30
       0 2756.29     9.9 2754.58    19.8  2754.8    39.5 2753.06    59.2 2750.42
    69.1 2748.23    98.8 2739.56   128.4 2729.49   138.2 2728.29   148.1  2725.8
   177.8 2714.84   227.1 2698.72     237 2695.75   246.9  2694.8   266.6  2688.7
   286.4 2680.83   296.3 2680.49   306.1  2680.4   554.3  2680.4   584.2 2680.53
   594.1 2681.77   614.1  2686.3     624  2689.6     644  2697.8   663.9 2701.56
   743.6 2728.82   763.5 2737.14   773.5 2738.42   783.5 2740.88   823.3 2754.19
#Mann= 3 , 0 , 0
       0      .1       0   296.3    .045       0   554.3      .1       0
Bank Sta=296.3,554.3
XS Rating Curve= 0 ,0
Exp/Cntr=0.3,0.1

Type RM Length L Ch R = 1 ,64.5    ,55.3,64.3,73.3
XS GIS Cut Line= 2
     1953614.412      249413.521     1953604.822      250244.977
#Sta/Elev= 30
       0 2731.55    19.8 2725.73    39.6 2720.47    59.4 2715.92    79.2 2712.28
    89.1 2712.26   138.6 2704.74   168.3 2699.13   178.2 2698.93   257.4 2685.64
   267.3 2685.34   277.2 2684.18   287.1 2682.12     297 2680.68   306.9  2680.4
   436.4  2680.4   554.3 2680.44   564.2 2681.24   633.5 2697.82   643.4 2699.24
   653.3  2700.1   673.1 2705.05     683 2707.85   722.6 2720.53   732.5 2723.18
   742.4 2724.25     782 2741.52   811.7 2753.47   821.6 2756.67   831.5 2757.14
#Mann= 3 , 0 , 0
       0      .1       0   306.9    .045       0   436.4      .1       0
Bank Sta=306.9,436.4
XS Rating Curve= 0 ,0
Exp/Cntr=0.3,0.1

Chan Stop Cuts=-1
Use User Specified Reach Order=0
Composite Channel Slope=5